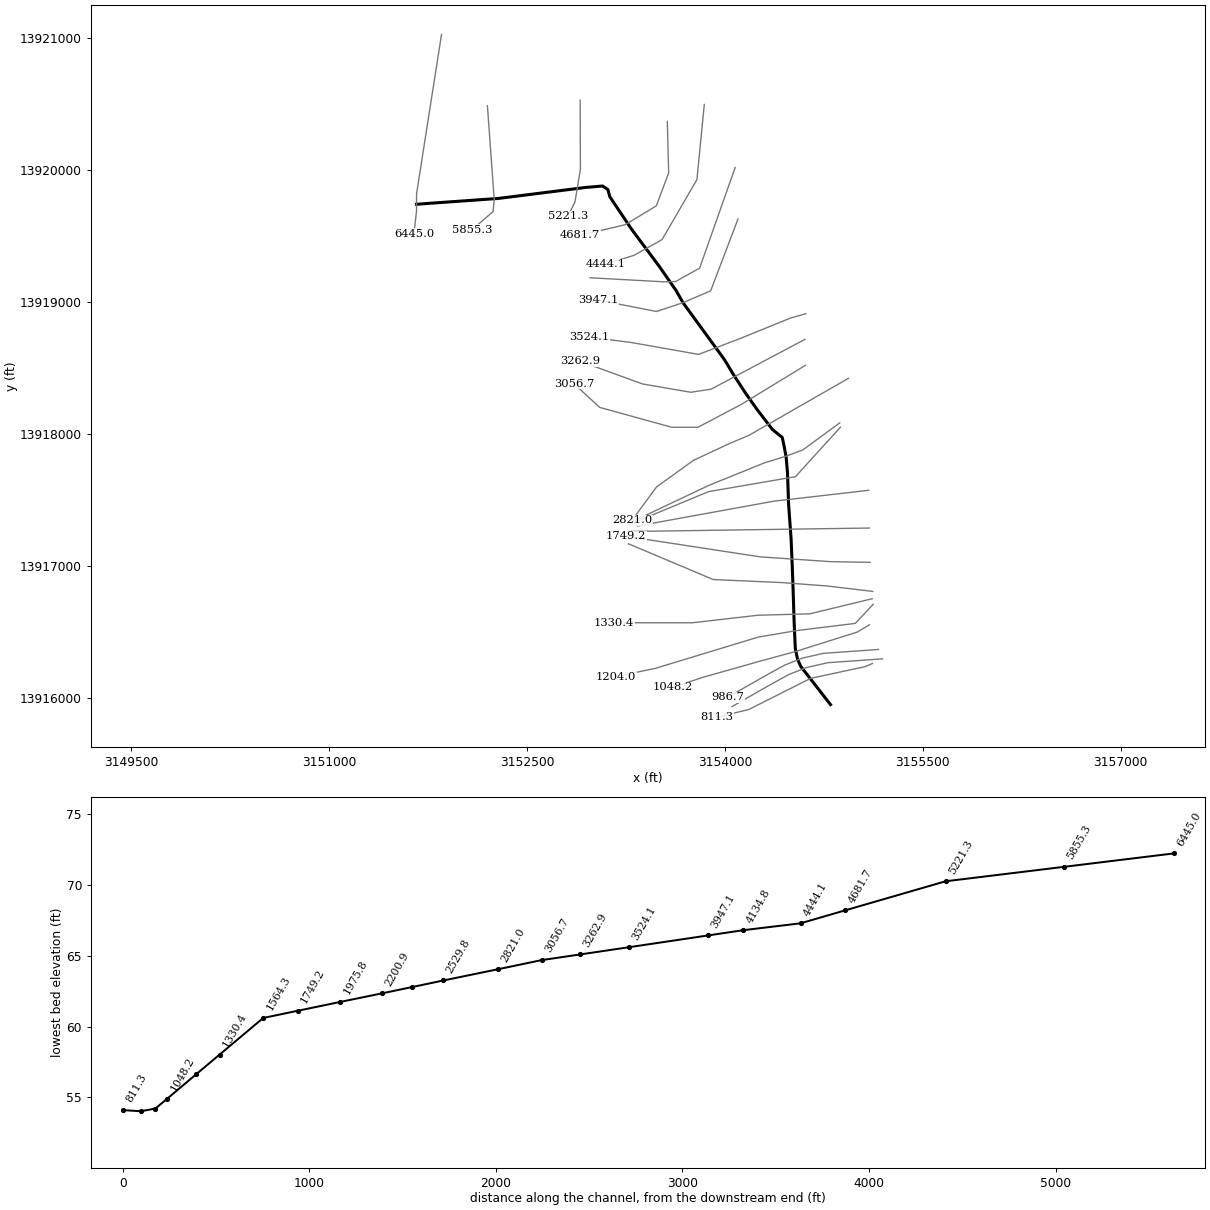
--- P130-03-01.PRJ (project) ---

Proj Title=P130-03-01
Current Plan=p02
Default Exp/Contr=.3,.1
English Units
Geom File=g01
Flow File=f01
Flow File=f02
Plan File=p01
Plan File=p02
Y Axis Title=Elevation
X Axis Title(PF)=Main Channel Distance
X Axis Title(XS)=Station
BEGIN DESCRIPTION:
Greens Bayou Watershed
Tributary 0.55 to Tributary 3.19 to Garners Bayou
HCFCD Unit P130-03-01
Flood Hazard Model
10, 2, 1, 0.2% Event
Filename P130-03-01.prj
Prepared by:  Watershed Concepts  Date:
Reviewed by:                      Date:
STATUS FINAL
END DESCRIPTION:
DSS Export Rating Curves= 0
DSS Export Rating Curve Sorted= 0
DSS Export Volume Flow Curves= 0
DXF OffsetX= 0
DXF OffsetY= 0
DXF ScaleX= 1
DXF ScaleY= 10

--- P130-03-01.p02 (plan) ---

Plan Title=Floodway
Version=Version 3.0.1  Mar 2001
Short Identifier=Floodway0607
Geom File=g01
Flow File=f02
Subcritical Flow
K Sum by GR= 0
Std Step Tol= 0.01
Critical Tol= 0.01
Num of Std Step Trials= 20
Max Error Tol= 0.3
Flow Tol Ratio= 0.001
Split Flow NTrial= 30
Split Flow Tol= 0.02
Split Flow Ratio= 0.02
Log Output Level= 0
Friction Slope Method= 1
Unsteady Friction Slope Method= 2
Parabolic Critical Depth
Global Vel Dist= 0 , 0 , 0
Global Log Level= 0
CheckData=True
Encroach Param=-1 ,0,0, 2
Encroach River=P130-03-01
Encroach Reach=Reach - 1
Encroach Node=6445.0
       1  4984.7  5010.8
Encroach Node=5855.3
       1  4963.1  5036.1
Encroach Node=5221.3
       1  4957.9    5035
Encroach Node=4681.7
       1  4945.3  5022.1
Encroach Node=4444.1
       1    4992 5007.83
Encroach Node=4134.8
       1    4992  5007.5
Encroach Node=3947.1
       1  4990.8    5032
Encroach Node=3524.1
       1    4985    5085
Encroach Node=3262.9
       1  4989.1    5081
Encroach Node=3056.7
       1  4989.1 5082.75
Encroach Node=2821.0
       1    4985    5058
Encroach Node=2529.8
       1    4975    5036
Encroach Node=2364.1
       1    4985  5014.7
Encroach Node=2200.9
       1    4990  5017.5
Encroach Node=1975.8
       1    4990  5030.9
Encroach Node=1749.2
       1    4980    5032
Encroach Node=1564.3
       1    4985    5023
Encroach Node=1330.4
       1  4991.5  5012.2
Encroach Node=1204.0
       1  4969.6  5028.7
Encroach Node=1048.2
       1  4969.6  5029.7
Encroach Node=986.7
       1  4969.6  5028.7
Encroach Node=947.7
       1  4969.6  5028.7
Encroach Node=908.7
       1  4969.6  5028.7
Encroach Node=811.3
       1  4969.6  5028.7
Encroach Reach=P130-03-01_0008
Encroach Node=6445.0
       1  4984.7  5010.8
Encroach Node=5855.3
       1  4963.1  5036.1
Encroach Node=5221.3
       1  4957.9    5035
Encroach Node=4681.7
       1  4945.3  5022.1
Encroach Node=4444.1
       1    4992 5007.83
Encroach Node=4134.8
       1    4992  5007.5
Encroach Node=3947.1
       1  4990.8    5032
Encroach Node=3524.1
       1    4985    5085
Encroach Node=3262.9
       1  4989.1    5081
Encroach Node=3056.7
       1  4989.1 5082.75
Encroach Node=2821.0
       1    4985    5058
Encroach Node=2529.8
       1    4975    5036
Encroach Node=2364.1
       1    4985  5014.7
Encroach Node=2200.9
       1    4990  5017.5
Encroach Node=1975.8
       1    4990  5030.9
Encroach Node=1749.2
       1    4980    5032
Encroach Node=1564.3
       1    4985    5023
Encroach Node=1330.4
       1  4991.5  5012.2
Encroach Node=1204.0
       1  4969.6  5028.7
Encroach Node=1048.2
       1  4969.6  5029.7
Encroach Node=986.7
       1  4969.6  5028.7
Encroach Node=947.7
       1  4969.6  5028.7
Encroach Node=908.7
       1  4969.6  5028.7
Encroach Node=811.3
       1  4969.6  5028.7
Computation Interval=1HOUR
Output Interval=1HOUR
Run HTab= 0
Run UNet= 0
Run PostProcess= 0
UNET Theta= 1
UNET ZTol= 0.02
UNET ZSATol= 0.05
UNET MxIter= 20
UNET MaxInSteps= 1
UNET DtIC= 0
UNET DtMin= 0
UNET MaxCRTS= 20
UNET WFStab= 2
UNET SFStab= 1
UNET WFX= 1
UNET SFX= 1
UNET Convert EG Bridges=-1
UNET Use Existing IB Tables=-1
Instantaneous Interval=1HOUR
Write IC File= 0
IC Time=0
Write Velocity= 0
Write Detailed= 0

--- P130-03-01.p01 (plan) ---

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Plan Title=FEMA Effective June 2007
Short Identifier=FEMAeff0607
Geom File=g01
Flow File=f01
Encroach Param=-1 ,0,0, 0

--- P130-03-01.f02 (steady flow) ---

Flow Title= Floodway
Number of Profiles= 2
Profile Names=1PCT_100yr, 1PCTFloodway_100yrFW
River Rch & RM=P130-03-01,P130-03-01_0008,6445.0
     146     146
River Rch & RM=P130-03-01,P130-03-01_0008,5855.3
     183     183
River Rch & RM=P130-03-01,P130-03-01_0008,5221.3
     227     227
River Rch & RM=P130-03-01,P130-03-01_0008,4444.1
     270     270
River Rch & RM=P130-03-01,P130-03-01_0008,4134.8
     325     325
River Rch & RM=P130-03-01,P130-03-01_0008,3524.1
     359     359
River Rch & RM=P130-03-01,P130-03-01_0008,3056.7
     375     375
River Rch & RM=P130-03-01,P130-03-01_0008,2821
     421     421
River Rch & RM=P130-03-01,P130-03-01_0008,2529.8
     432     432
River Rch & RM=P130-03-01,P130-03-01_0008,2364.1
     494     494
River Rch & RM=P130-03-01,P130-03-01_0008,1564.3
     524     524
River Rch & RM=P130-03-01,P130-03-01_0008,1204
     543     543
River Rch & RM=P130-03-01,P130-03-01_0008,986.7
     559     559
Boundary for River Rch & Prof#=P130-03-01,P130-03-01_0008, 1
Up Type= 0
Dn Type= 3
Dn Slope= 0.00390
Boundary for River Rch & Prof#=P130-03-01,P130-03-01_0008, 2
Up Type= 0
Dn Type= 1
Dn Known WS=60.54

--- P130-03-01.f01 (steady flow) ---

Flow Title= FEMA Effective June 2007
Number of Profiles= 4
Profile Names=10PCT_10yr, 2PCT_50yr, 1PCT_100yr, 0.2PCT_500yr
River Rch & RM=P130-03-01,P130-03-01_0008,6445.0
      86     126     146     204
River Rch & RM=P130-03-01,P130-03-01_0008,5855.3
     107     157     183     255
River Rch & RM=P130-03-01,P130-03-01_0008,5221.3
     133     196     227     317
River Rch & RM=P130-03-01,P130-03-01_0008,4444.1
     158     232     270     376
River Rch & RM=P130-03-01,P130-03-01_0008,4134.8
     191     279     325     453
River Rch & RM=P130-03-01,P130-03-01_0008,3524.1
     211     309     359     501
River Rch & RM=P130-03-01,P130-03-01_0008,3056.7
     220     322     375     523
River Rch & RM=P130-03-01,P130-03-01_0008,2821
     247     362     421     587
River Rch & RM=P130-03-01,P130-03-01_0008,2529.8
     254     372     432     603
River Rch & RM=P130-03-01,P130-03-01_0008,2364.1
     290     425     494     689
River Rch & RM=P130-03-01,P130-03-01_0008,1564.3
     308     451     524     731
River Rch & RM=P130-03-01,P130-03-01_0008,1204
     319     468     543     758
River Rch & RM=P130-03-01,P130-03-01_0008,986.7
     328     481     559     780
Boundary for River Rch & Prof#=P130-03-01,P130-03-01_0008, 1
Up Type= 0
Dn Type= 3
Dn Slope= 0.00390
Boundary for River Rch & Prof#=P130-03-01,P130-03-01_0008, 2
Up Type= 0
Dn Type= 3
Dn Slope= 0.00390
Boundary for River Rch & Prof#=P130-03-01,P130-03-01_0008, 3
Up Type= 0
Dn Type= 3
Dn Slope= 0.00390
Boundary for River Rch & Prof#=P130-03-01,P130-03-01_0008, 4
Up Type= 0
Dn Type= 3
Dn Slope= 0.00390

--- P130-03-01.g01 (geometry) ---

Geom Title=P130-03-01 June 2007
Version=Version 3.0.1  Mar 2001

River Reach=P130-03-01      ,P130-03-01_0008
Reach XY= 30
      3151663.36     13919741.64      3151761.75       13919749.
      3152284.25       13919786.      3152942.18     13919868.96
      3153073.08     13919880.05      3153113.02     13919853.43
      3153128.55     13919797.96      3153294.96     13919549.45
      3153503.53     13919269.88        3153630.     13919087.94
      3153683.25     13918994.75      3153995.25     13918566.29
      3154061.85     13918455.87      3154151.42       13918318.
      3154182.27     13918273.96      3154241.41     13918189.92
      3154359.92     13918035.24      3154434.39     13917974.82
        3154448.     13917911.84      3154463.57     13917828.79
      3154474.18     13917710.04      3154482.66      13917468.3
      3154501.74     13917203.22      3154510.23     13917001.77
      3154516.59     13916827.88      3154525.07     13916560.69
      3154533.55     13916374.08       3154550.5       13916294.
      3154575.25       13916239.       3154800.4     13915949.92

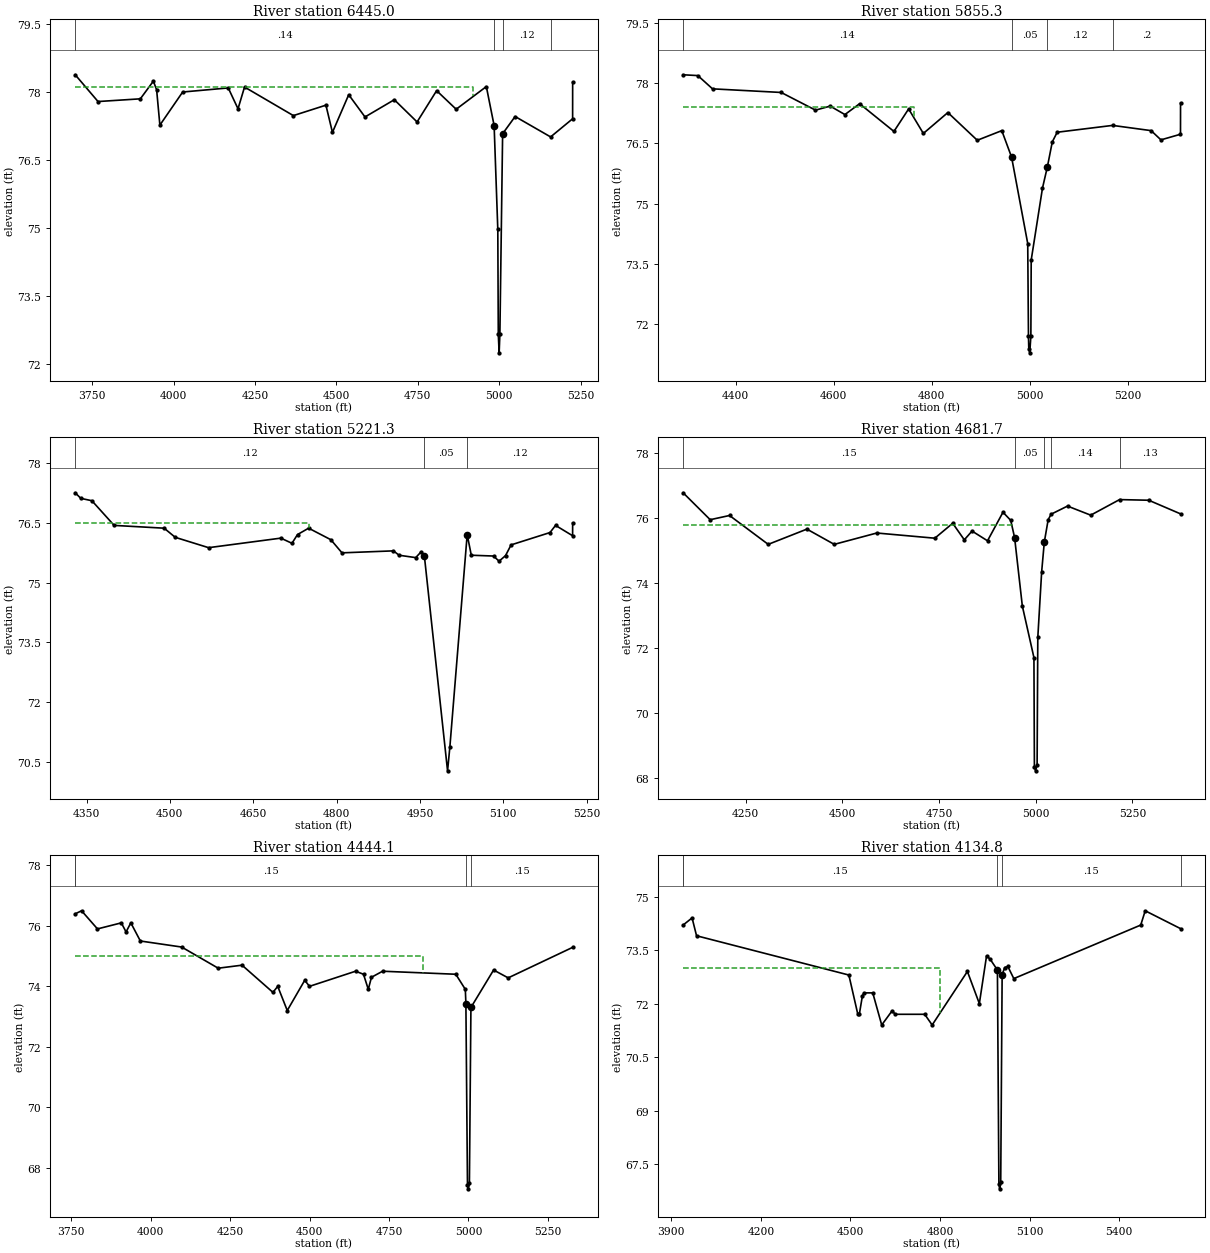
Type RM Length L Ch R = 1 ,6445.0  ,589.8,589.7,587.7
BEGIN DESCRIPTION:
Cross Section 6445.0
END DESCRIPTION:
XS GIS Cut Line= 4
      3151852.62      13921028.8      3151663.36     13919820.89
      3151663.36     13919692.51      3151643.67     13919517.01
#Sta/Elev= 30
  3698.1   78.37  3768.1   77.78  3898.1   77.84  3938.1   78.23  3948.1   78.04
  3958.1   77.26  4028.1   77.99  4168.1   78.08  4198.1   77.62  4218.1    78.1
  4368.1   77.47  4468.1    77.7  4488.1    77.1  4538.1   77.93  4588.1   77.44
  4678.1   77.82  4748.1   77.33  4808.1   78.02  4868.1   77.61  4960.8   78.11
  4984.7   77.25    4996   74.96  4997.5   72.65  5000.1   72.24  5002.4   72.65
  5010.8   77.07  5049.2   77.45  5158.2      77  5225.8    77.4  5225.9    78.2
#Mann= 4 , 1 , 0
  3698.1     .14       0  4984.7     .05       0  5010.8     .12       0
  5158.2     .12       0
#XS Ineff= 2 , 0
       0  4920.8    78.1               0
Permanent Ineff=
       F       F
Bank Sta=4984.7,5010.8
XS Rating Curve= 0
Exp/Cntr=.3,.1

Type RM Length L Ch R = 1 ,5855.3  ,640.6,634,627.9
BEGIN DESCRIPTION:
Cross Section 5855.3-Interpolated
END DESCRIPTION:
XS GIS Cut Line= 4
      3152200.35     13920488.73      3152251.96     13919777.63
      3152243.14     13919686.49      3152084.39     13919549.07
#Sta/Elev= 30
  4293.1   78.21  4323.1   78.19  4353.1   77.86  4493.1   77.77  4563.1   77.33
  4593.1   77.43  4623.1   77.22  4653.1   77.49  4723.1    76.8  4753.1   77.36
  4783.1   76.75  4833.1   77.27  4893.1   76.58  4943.1   76.82  4963.1   76.16
    4996   74.01  4997.5    71.7  4998.2   71.39  5000.1   71.29  5002.4    71.7
  5003.1    73.6  5026.1   75.39  5036.1   75.92  5046.1   76.54  5056.1   76.78
  5169.1   76.95  5247.7   76.82  5267.7   76.59  5307.6   76.73  5307.7    77.5
#Mann= 4 , 1 , 0
  4293.1     .14       0  4963.1     .05       0  5036.1     .12       0
  5169.1      .2       0
#XS Ineff= 2 , 0
       0  4763.1    77.4               0
Permanent Ineff=
       F       F
Bank Sta=4963.1,5036.1
XS Rating Curve= 0
Exp/Cntr=.3,.1

Type RM Length L Ch R = 1 ,5221.3  ,560,539.6,485.4
BEGIN DESCRIPTION:
Cross Section 5221.3
END DESCRIPTION:
XS GIS Cut Line= 4
      3152903.16      13920529.5      3152905.01     13920006.79
      3152863.66     13919758.68      3152809.67     13919650.71
#Sta/Elev= 30
  4329.7   77.26  4339.7   77.12  4359.7   77.06  4399.7   76.44  4489.7   76.37
  4509.7   76.14  4569.7   75.88  4699.7   76.12  4719.7   75.99  4729.7   76.21
  4749.7   76.37  4789.7   76.08  4809.7   75.75  4902.4    75.8  4912.4   75.69
  4942.4   75.63  4952.4   75.78  4957.9   75.68  4999.7   70.27  5003.9   70.88
    5035   76.21  5042.4   75.69  5082.4   75.67  5092.4   75.54    5104   75.68
    5114   75.95    5184   76.26    5194   76.44  5224.7   76.18  5224.8    76.5
#Mann= 3 , 1 , 0
  4329.7     .12       0  4957.9     .05       0    5035     .12       0
#XS Ineff= 2 , 0
       0  4749.7    76.5               0
Permanent Ineff=
       F       F
Bank Sta=4957.9,5035
XS Rating Curve= 0
Exp/Cntr=.3,.1

Type RM Length L Ch R = 1 ,4681.7  ,237.1,237.6,241.9
BEGIN DESCRIPTION:
Cross Section 4681.7-Interpolated
END DESCRIPTION:
XS GIS Cut Line= 5
      3153563.55     13920369.65      3153573.83     13919979.07
      3153480.35     13919729.79      3153243.53     13919586.46
      3152900.78     13919505.44
#Sta/Elev= 30
  4088.4   76.78  4158.4   75.95  4208.4   76.08  4308.4   75.19  4408.4   75.66
  4479.1   75.19  4589.1   75.54  4739.1   75.38  4785.3   75.84  4815.3   75.33
  4835.3    75.6  4875.3    75.3  4915.3   76.18  4935.3   75.93  4945.3    75.4
  4965.3   73.29  4995.3    71.7  4996.5   68.34  4999.4   68.21  5003.5   68.39
  5005.3   72.32  5015.3   74.35  5022.1   75.26  5032.1   75.95  5039.7   76.12
  5082.1   76.37  5142.1   76.09  5216.7   76.57  5292.1   76.55  5374.3   76.13
#Mann= 5 , 1 , 0
  4088.4     .15       0  4945.3     .05       0  5022.1     .15       0
  5039.7     .14       0  5216.7     .13       0
#XS Ineff= 2 , 0
       0  4939.6    75.8               0
Permanent Ineff=
       F       F
Bank Sta=4945.3,5022.1
XS Rating Curve= 0
Exp/Cntr=.3,.1

Type RM Length L Ch R = 1 ,4444.1  ,324.1,309.3,288.6
BEGIN DESCRIPTION:
Cross Section 4444.1 - Interpolated
END DESCRIPTION:
XS GIS Cut Line= 5
      3153843.86     13920498.15      3153787.93     13919928.63
      3153523.97     13919474.28      3153312.41      13919355.3
      3153097.56     13919288.36
#Sta/Elev= 30
  3762.5    76.4  3782.5    76.5  3832.5    75.9  3907.5    76.1  3922.5    75.8
  3937.5    76.1  3967.5    75.5  4097.5    75.3  4212.5    74.6  4287.5    74.7
  4384.8    73.8  4399.8      74  4429.8    73.2  4484.8    74.2  4499.8      74
  4644.8    74.5  4669.8    74.4  4684.8    73.9  4694.8    74.3  4729.8    74.5
  4960.2    74.4  4990.2    73.9    4992   73.43 4996.96   67.43 4999.48    67.3
 5003.05   67.48 5007.83    73.3  5079.2   74.54  5125.1   74.28    5328   75.29
#Mann= 4 , 1 , 0
  3762.5      .2       0  3762.5     .15       0    4992     .05       0
 5007.83     .15       0
#XS Ineff= 2 , 0
       0    4858      75               0
Permanent Ineff=
       F       F
Bank Sta=4992,5007.83
XS Rating Curve= 0
Exp/Cntr=.3,.1

Type RM Length L Ch R = 1 ,4134.8  ,176.5,187.7,197.8
BEGIN DESCRIPTION:
Cross Section 4134.8-SKEWED AT 30 DEGREES
END DESCRIPTION:
XS GIS Cut Line= 6
      3154077.77     13920020.16      3153808.27     13919257.43
      3153683.16     13919188.23      3153627.33     13919156.18
      3153536.35     13919154.11      3152978.92     13919184.71
#Sta/Elev= 29
  3939.6    74.2  3969.6    74.4  3984.6    73.9  4494.6    72.8  4524.6    71.7
  4529.6    71.7  4539.6    72.2  4544.6    72.3  4574.6    72.3  4604.6    71.4
  4639.6    71.8  4649.6    71.7  4748.5    71.7  4773.5    71.4  4891.5    72.9
  4931.5      72 4955.72   73.34 4967.98   73.24    4992   72.94 4996.96   66.94
 4999.48   66.81 5003.05   66.99 5007.83   72.81 5016.44   73.01 5026.88   73.04
  5046.9    72.7  5471.9    74.2  5486.9    74.6  5605.2    74.1
#Mann= 5 , 1 , 0
  3939.6      .2       0  3939.6     .15       0    4992     .05       0
 5007.83     .15       0  5605.2      .2       0
#XS Ineff= 2 , 0
       0    4800      73               0
Permanent Ineff=
       F       F
Bank Sta=4992,5007.83
XS Rating Curve= 0
Exp/Cntr=.3,.1

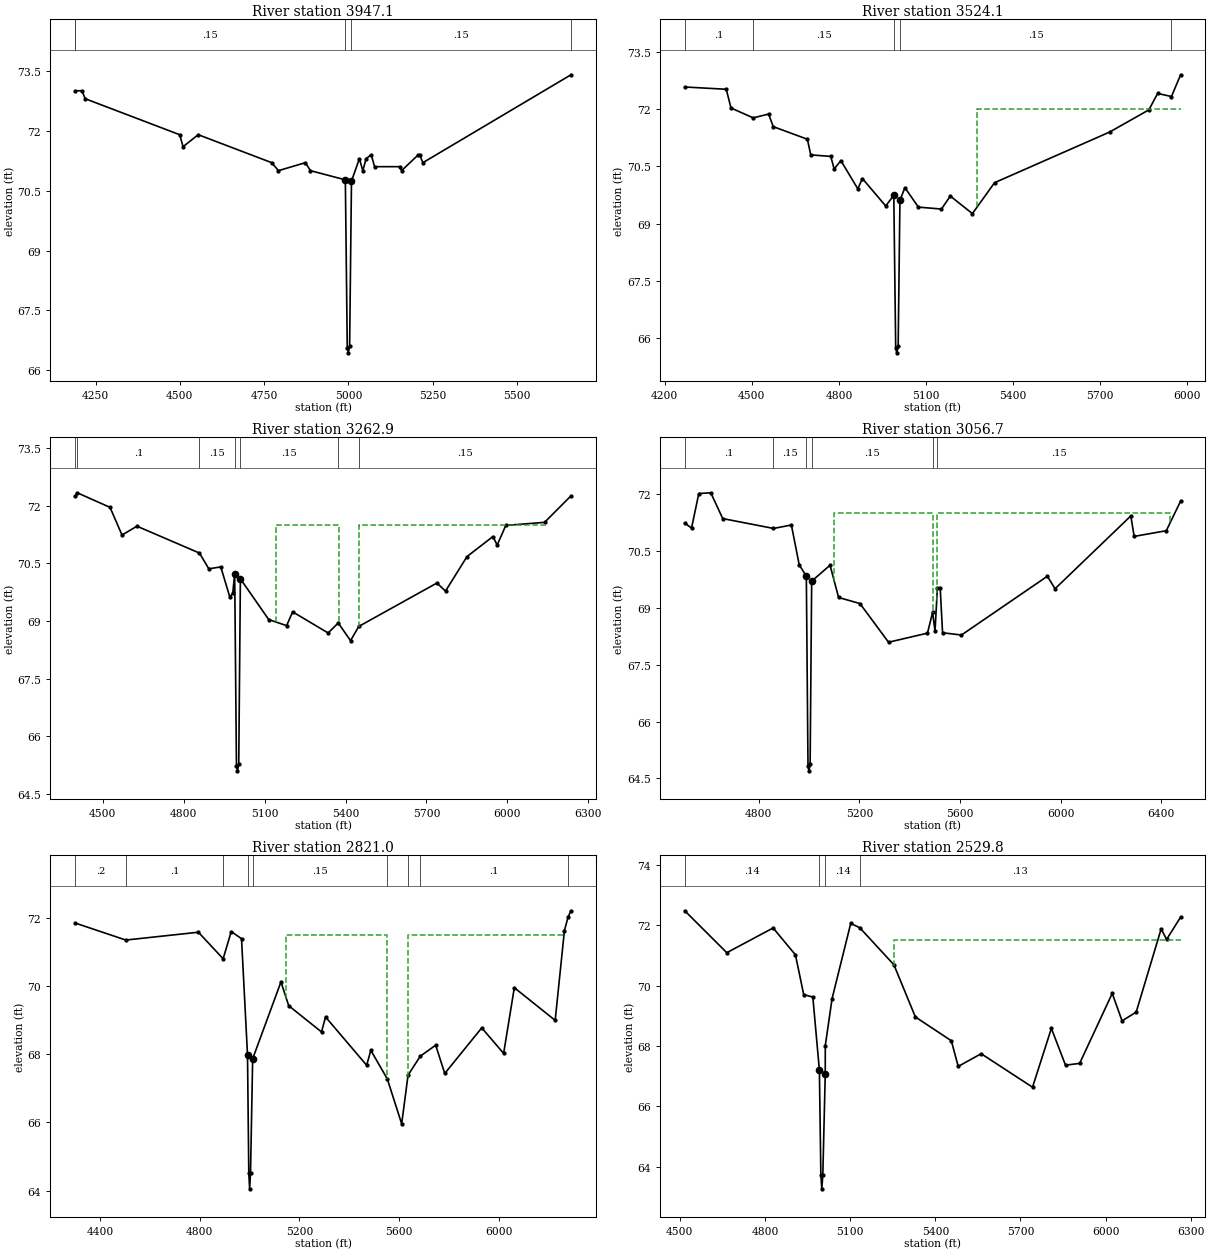
Type RM Length L Ch R = 1 ,3947.1  ,423.5,423,390.7
BEGIN DESCRIPTION:
Cross Section 3947.1 - Interpolated
END DESCRIPTION:
XS GIS Cut Line= 5
      3154099.31     13919630.12      3153891.84     13919085.54
      3153680.22     13918995.07      3153482.56     13918929.27
      3153041.76     13919015.05
#Sta/Elev= 26
  4189.6      73  4209.6      73  4219.6    72.8  4499.6    71.9  4509.6    71.6
  4554.6    71.9  4772.4    71.2  4792.4      71  4872.4    71.2  4887.4      71
  4990.8   70.77  4996.5   66.57  4999.4   66.44  5003.5   66.62    5009   70.74
  5032.5    71.3  5042.5      71  5052.5    71.3  5067.5    71.4  5077.5    71.1
  5152.5    71.1  5157.5      71  5207.5    71.4  5210.8    71.4  5220.8    71.2
  5659.9    73.4
#Mann= 5 , 1 , 0
  4189.6      .2       0  4189.6     .15       0  4990.8     .05       0
    5009     .15       0  5659.9      .2       0
Bank Sta=4990.8,5009
XS Rating Curve= 0
Exp/Cntr=.3,.1

Type RM Length L Ch R = 1 ,3524.1  ,259.5,261.2,295.7
BEGIN DESCRIPTION:
Cross Section 3552.3-Interpolated
END DESCRIPTION:
XS GIS Cut Line= 6
      3154614.32     13918912.55      3154496.66      13918879.3
      3154119.21     13918725.97      3153800.74     13918604.08
      3153290.15      13918694.3        3152974.     13918735.09
#Sta/Elev= 30
  4269.2   72.58  4412.1   72.52  4428.3   72.03  4504.8   71.77  4557.9   71.87
    4574   71.54  4691.5   71.21  4703.1    70.8  4772.1   70.76  4783.7   70.43
  4806.8   70.65  4865.2   69.91    4881   70.18  4961.3   69.46  4989.1   69.74
  4995.7   65.74  4999.5   65.61  5004.2   65.79  5010.3   69.61  5027.4   69.94
  5073.9   69.43  5153.3   69.38  5183.8   69.72  5259.9   69.26  5336.1   70.07
    5733    71.4  5867.7   71.98    5898   72.41  5945.5   72.33  5977.1    72.9
#Mann= 5 ,-1 , 0
  4269.2      .1       0  4504.8     .15       0  4989.1     .05       0
  5010.3     .15       0  5945.5      .2       0
#XS Ineff= 2 , 0
       0                    5276       0      72
Permanent Ineff=
       F       F
Bank Sta=4989.1,5010.3
XS Rating Curve= 0
Exp/Cntr=.3,.1

Type RM Length L Ch R = 1 ,3262.9  ,204.8,206.2,246
BEGIN DESCRIPTION:
Cross Section 3262.9 - Interpolated
END DESCRIPTION:
XS GIS Cut Line= 5
      3154606.75      13918718.1       3153895.1     13918340.65
      3153741.76     13918317.06      3153376.11     13918379.97
      3152900.37     13918552.97
#Sta/Elev= 30
  4397.8   72.25  4405.6   72.34  4527.1   71.96  4571.5   71.24    4627   71.47
  4858.6   70.77  4893.3   70.36  4937.6   70.41  4970.9   69.63    4982   69.72
  4989.1   70.23  4995.7   65.23  4999.5    65.1  5004.2   65.28  5010.3    70.1
  5115.2   69.04  5181.7   68.88    5204   69.24  5335.5   68.69    5373   68.95
  5418.6   68.49  5449.1   68.86  5738.7   69.99  5770.6   69.78  5850.4   70.68
  5946.2    71.2  5962.1   70.98  5994.1   71.49  6137.7   71.57  6235.7   72.26
#Mann= 7 ,-1 , 0
  4397.8      .2       0  4405.6      .1       0  4858.6     .15       0
  4989.1     .05       0  5010.3     .15       0    5373     .05       0
  5449.1     .15       0
#XS Ineff= 2 ,-1
    5142 5375.29    71.5  5448.1    6150    71.5
Permanent Ineff=
       F       F
Bank Sta=4989.1,5010.3
XS Rating Curve= 0
Exp/Cntr=.3,.1

Type RM Length L Ch R = 1 ,3056.7  ,234.9,235.7,246
BEGIN DESCRIPTION:
Cross Section 3056.7
END DESCRIPTION:
XS GIS Cut Line= 6
      3154610.68     13918521.51      3154127.08     13918226.63
      3153795.98     13918051.93      3153596.74     13918051.93
      3153051.63      13918202.3      3152856.35       13918381.
#Sta/Elev= 30
  4506.1   71.23    4533    71.1  4561.8   72.01  4609.4   72.03  4656.9   71.35
  4858.6   71.09  4929.7   71.18  4960.8   70.13  4989.1   69.83  4995.7   64.83
  4999.5    64.7  5004.2   64.88  5010.3    69.7  5083.3   70.12  5117.3   69.27
  5202.1   69.11  5315.8   68.09  5470.4   68.33  5490.9   68.88  5500.4   68.38
  5509.8   69.52  5520.9   69.53  5530.4   68.34  5605.4   68.28  5946.8   69.83
  5977.3    69.5  6278.4   71.42  6291.7   70.88  6419.3   71.03  6476.3   71.81
#Mann= 6 ,-1 , 0
  4506.1      .1       0  4858.6     .15       0  4989.1     .05       0
  5010.3     .15       0  5490.9     .05       0  5509.8     .15       0
#XS Ineff= 2 ,-1
    5101  5490.6    71.5    5507    6434    71.5
Permanent Ineff=
       F       F
Bank Sta=4989.1,5010.3
XS Rating Curve= 0
Exp/Cntr=.3,.1

Type RM Length L Ch R = 1 ,2821.0  ,293.4,291.2,232.9
BEGIN DESCRIPTION:
Cross Section 2821.0-Interpolated
END DESCRIPTION:
XS GIS Cut Line= 6
      3154937.02     13918423.22      3154182.12     13917990.73
      3154032.71     13917927.82      3153760.98     13917800.77
      3153481.99     13917599.68      3153295.63      13917346.3
#Sta/Elev= 30
  4299.6   71.86  4503.1   71.36  4794.4   71.59  4893.7   70.81  4926.2   71.61
  4967.5    71.4  4991.5   67.99  4996.7   64.51    5000   64.05  5003.6   64.51
  5012.2   67.87  5125.8   70.13    5157   69.43  5288.6   68.66  5304.8    69.1
  5469.9   67.68  5486.5   68.12  5552.7   67.28  5610.4   65.96    5636   67.39
  5685.4   67.95  5746.9   68.27  5783.4   67.44  5931.8   68.78  6019.7   68.03
  6062.6   69.96  6226.6      69  6263.8   71.64  6278.5   72.04  6290.1   72.22
#Mann= 9 ,-1 , 0
  4299.6      .2       0  4503.1      .1       0  4893.7     .14       0
  4991.5     .05       0  5012.2     .15       0  5552.7     .05       0
    5636     .15       0  5685.4      .1       0  6278.5     .14       0
#XS Ineff= 2 ,-1
    5148    5553    71.5    5635    6264    71.5
Permanent Ineff=
       F       F
Bank Sta=4991.5,5012.2
XS Rating Curve= 0
Exp/Cntr=.3,.1

Type RM Length L Ch R = 1 ,2529.8  ,171.1,165.7,80
BEGIN DESCRIPTION:
Cross Section 2529.8-Interpolated
END DESCRIPTION:
XS GIS Cut Line= 6
      3154870.02     13918084.92      3154591.02     13917880.64
      3154465.81     13917833.43      3154300.07     13917782.34
      3153876.96     13917610.96      3153301.07     13917338.14
#Sta/Elev= 30
  4517.3   72.48  4665.3   71.09  4828.5   71.91  4907.1   71.02  4936.3    69.7
  4968.4   69.62  4991.5    67.2  4996.7   63.72    5000   63.26  5003.6   63.72
  5012.2   67.08  5012.3   68.01  5036.3   69.57  5101.9   72.06  5133.5   71.92
    5254   70.69  5329.6   68.96  5456.3   68.17  5480.6   67.32  5561.5   67.74
  5742.4   66.63  5808.8   68.58  5858.6   67.36  5908.4   67.42  6023.2   69.74
  6057.8   68.83  6107.6   69.12  6195.5   71.88  6214.7   71.53  6264.1   72.27
#Mann= 4 ,-1 , 0
  4517.3     .14       0  4991.5     .05       0  5012.2     .14       0
  5133.5     .13       0
#XS Ineff= 2 , 0
       0                    5256       0    71.5
Permanent Ineff=
       F       F
Bank Sta=4991.5,5012.2
XS Rating Curve= 0
Exp/Cntr=.3,.1

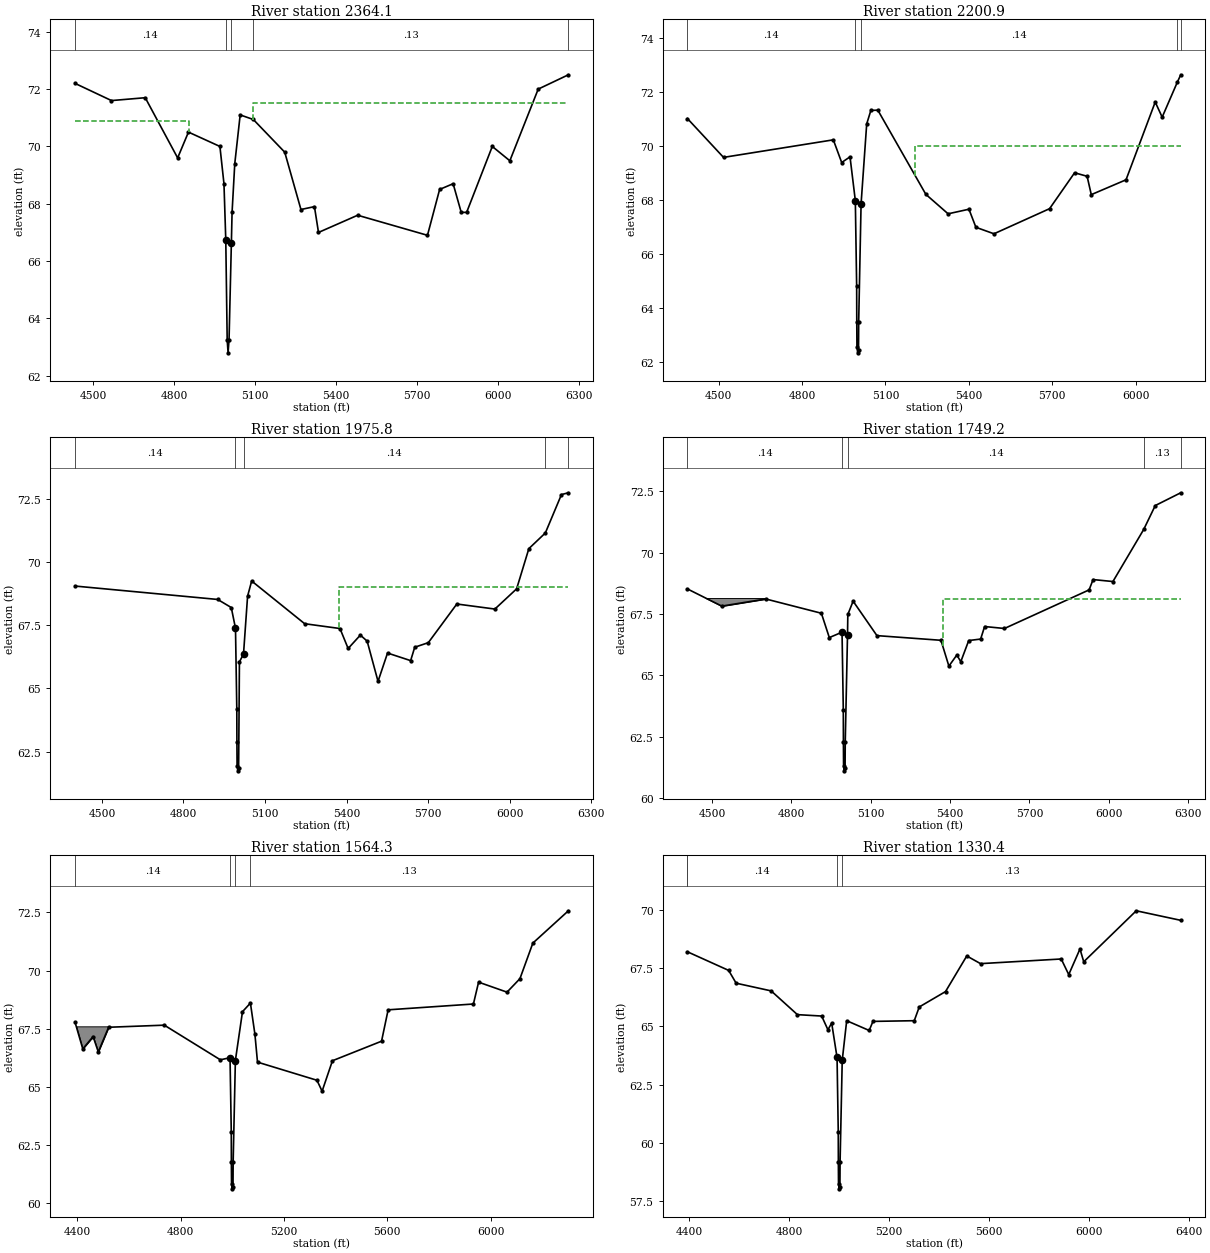
Type RM Length L Ch R = 1 ,2364.1  ,162.4,163.2,166.5
BEGIN DESCRIPTION:
Cross Section 2364.1-Interpolated
END DESCRIPTION:
XS GIS Cut Line= 4
       3154875.7     13918052.44      3154534.97     13917677.64
      3153876.22     13917564.06      3153274.26     13917314.19
#Sta/Elev= 30
  4433.3    72.2  4568.3    71.6  4693.3    71.7  4813.3    69.6  4853.3    70.5
  4969.8      70  4984.8    68.7  4991.5   66.74  4996.7   63.26    5000    62.8
  5003.6   63.26  5012.2   66.62  5014.8    67.7  5024.8    69.4  5044.8    71.1
  5093.5   70.94  5209.8    69.8  5269.8    67.8  5319.8    67.9  5334.8      67
  5479.8    67.6  5738.3    66.9  5783.3    68.5  5833.3    68.7  5863.3    67.7
  5883.3    67.7  5978.3      70  6043.3    69.5  6148.3      72  6260.1    72.5
#Mann= 5 ,-1 , 0
  4433.3     .14       0  4991.5     .05       0  5012.2     .14       0
  5093.5     .13       0  6260.1     .13       0
#XS Ineff= 2 , 0
       0    4855    70.9    5094       0    71.5
Permanent Ineff=
       F       F
Bank Sta=4991.5,5012.2
XS Rating Curve= 0
Exp/Cntr=.3,.1

Type RM Length L Ch R = 1 ,2200.9  ,227.7,225.1,180.1
BEGIN DESCRIPTION:
Cross Section 2200.9 - Interpolated
END DESCRIPTION:
XS GIS Cut Line= 3
      3155089.98      13917574.3      3154366.96     13917491.08
      3153337.05     13917303.82
#Sta/Elev= 30
  4387.4   71.03  4517.4   69.59  4912.4   70.24  4942.4    69.4  4972.4   69.61
  4991.5   67.99  4996.3   64.81  4996.7   63.51  4997.3   62.56    5000   62.35
    5003   62.45  5003.6   63.51  5012.2   67.87  5032.4   70.83  5047.4   71.33
  5072.4   71.34  5245.2   68.22  5325.2    67.5  5400.2   67.67  5425.2      67
  5490.2   66.76  5690.2   67.69  5780.2   69.02  5825.2   68.89  5840.2   68.21
  5965.2   68.76  6070.2   71.64  6095.2   71.08  6150.3   72.39    6162   72.65
#Mann= 5 ,-1 , 0
  4387.4     .14       0  4991.5     .05       0  5012.2     .14       0
  6150.3     .13       0    6162     .13       0
#XS Ineff= 2 , 0
       0                    5207       0      70
Permanent Ineff=
       F       F
Bank Sta=4991.5,5012.2
XS Rating Curve= 0
Exp/Cntr=.3,.1

Type RM Length L Ch R = 1 ,1975.8  ,226,226.6,240.1
BEGIN DESCRIPTION:
Cross Section 1975.8 - Interpolated
END DESCRIPTION:
XS GIS Cut Line= 2
      3155095.19     13917288.22      3153279.83     13917262.21
#Sta/Elev= 30
    4401   69.05    4926   68.52    4976    68.2  4991.5   67.38  4996.3    64.2
  4996.7    62.9  4997.3   61.95    5000   61.74    5003   61.84    5006   66.05
    5021   66.36    5036   68.65    5051   69.25    5246   67.56    5376   67.37
    5406   66.58    5451   67.11    5476   66.87    5516   65.28    5551    66.4
    5636    66.1    5651   66.63    5701   66.81    5806   68.34    5946   68.14
    6026   68.94    6071   70.53  6131.7   71.15    6191   72.67  6216.5   72.74
#Mann= 5 ,-1 , 0
    4401     .14       0  4991.5     .05       0    5021     .14       0
  6131.7     .13       0  6216.5     .13       0
#XS Ineff= 2 , 0
       0                    5372       0      69
Permanent Ineff=
       F       F
Bank Sta=4991.5,5021
XS Rating Curve= 0
Exp/Cntr=.3,.1

Type RM Length L Ch R = 1 ,1749.2  ,184,184.9,211.5
BEGIN DESCRIPTION:
Cross Section 1749.2 - Interpolated
END DESCRIPTION:
XS GIS Cut Line= 4
      3155100.39     13917028.14       3154803.9     13917033.34
      3154268.13     13917069.75      3153248.62      13917225.8
#Sta/Elev= 30
  4406.9   68.52  4536.9   67.82  4703.4   68.11  4913.4   67.53  4943.4   66.54
  4991.5   66.76  4996.3   63.58  4996.7   62.28  4997.3   61.33    5000   61.12
    5003   61.22  5003.6   62.28  5012.2   66.64  5013.4   67.48  5033.4   68.02
  5123.4   66.62  5365.4   66.43  5395.4   65.38  5425.4   65.83  5440.4   65.56
  5470.4   66.42  5515.4   66.48  5530.4   66.99  5605.4   66.91  5925.4   68.48
  5940.4    68.9  6015.4   68.82  6131.9   70.94  6175.4   71.91  6271.8   72.43
#Mann= 5 ,-1 , 0
  4406.9     .14       0  4991.5     .05       0  5012.2     .14       0
  6131.9     .13       0  6271.8     .13       0
#XS Ineff= 2 , 0
       0                    5372       0    68.1
Permanent Ineff=
       F       F
#Block Obstruct= 2 , 0
       0    4700   68.15               0
Bank Sta=4991.5,5012.2
XS Rating Curve= 0
Exp/Cntr=.3,.1

Type RM Length L Ch R = 1 ,1564.3  ,232.2,233.9,267.4
BEGIN DESCRIPTION:
Cross Section 1564.3
END DESCRIPTION:
XS GIS Cut Line= 5
      3155120.23     13916808.09      3154777.17     13916848.93
      3154427.55     13916875.25      3153912.52     13916897.81
      3153269.67     13917168.48
#Sta/Elev= 30
  4391.7   67.78  4421.7   66.63  4461.7   67.16  4481.7    66.5  4521.7   67.56
  4737.2   67.65    4954   66.16  4991.5   66.25  4996.3   63.07  4996.7   61.77
  4997.3   60.82    5000   60.61    5003   60.71  5003.6   61.77  5012.2   66.13
  5039.7   68.23  5070.4    68.6  5087.8   67.26  5097.8   66.06  5327.8   65.28
  5347.8   64.81  5387.8   66.12  5577.8   66.96  5603.3   68.31  5933.3   68.56
  5953.3    69.5  6063.3   69.07  6113.3   69.65  6163.3   71.18  6300.8   72.57
#Mann= 4 ,-1 , 0
  4391.7     .14       0  4991.5     .05       0  5012.2     .14       0
  5070.4     .13       0
#XS Ineff= 2 , 0
       0                    5078       0      68
Permanent Ineff=
       F       F
#Block Obstruct= 2 , 0
       0    4520    67.6               0
Bank Sta=4991.5,5012.2
XS Rating Curve= 0
Exp/Cntr=.3,.1

Type RM Length L Ch R = 1 ,1330.4  ,123.3,126.4,132.1
BEGIN DESCRIPTION:
Cross Section 1330.4 - Interpolated
END DESCRIPTION:
XS GIS Cut Line= 5
      3155115.99     13916752.45      3154642.65     13916638.02
      3154252.53     13916627.61      3153753.18      13916570.4
      3153160.19      13916570.4
#Sta/Elev= 30
    4393    68.2    4558    67.4    4588   66.85    4728   66.52    4833    65.5
    4930   65.44    4955   64.85    4970   65.14  4991.5   63.66  4996.3   60.48
  4996.7   59.18  4997.3   58.23    5000   58.02    5003   58.12  5003.6   59.18
  5012.2   63.54    5030   65.24    5120   64.82    5135   65.21  5300.2   65.24
  5320.2   65.83  5425.2   66.49  5510.2   68.02  5565.2   67.69  5887.9   67.89
  5917.9   67.22  5962.9   68.32  5977.9   67.77  6187.9   69.96  6365.8   69.55
#Mann= 4 , 1 , 0
    4393      .2       0    4393     .14       0  4991.5     .05       0
  5012.2     .13       0
Bank Sta=4991.5,5012.2
XS Rating Curve= 0
Exp/Cntr=.3,.1

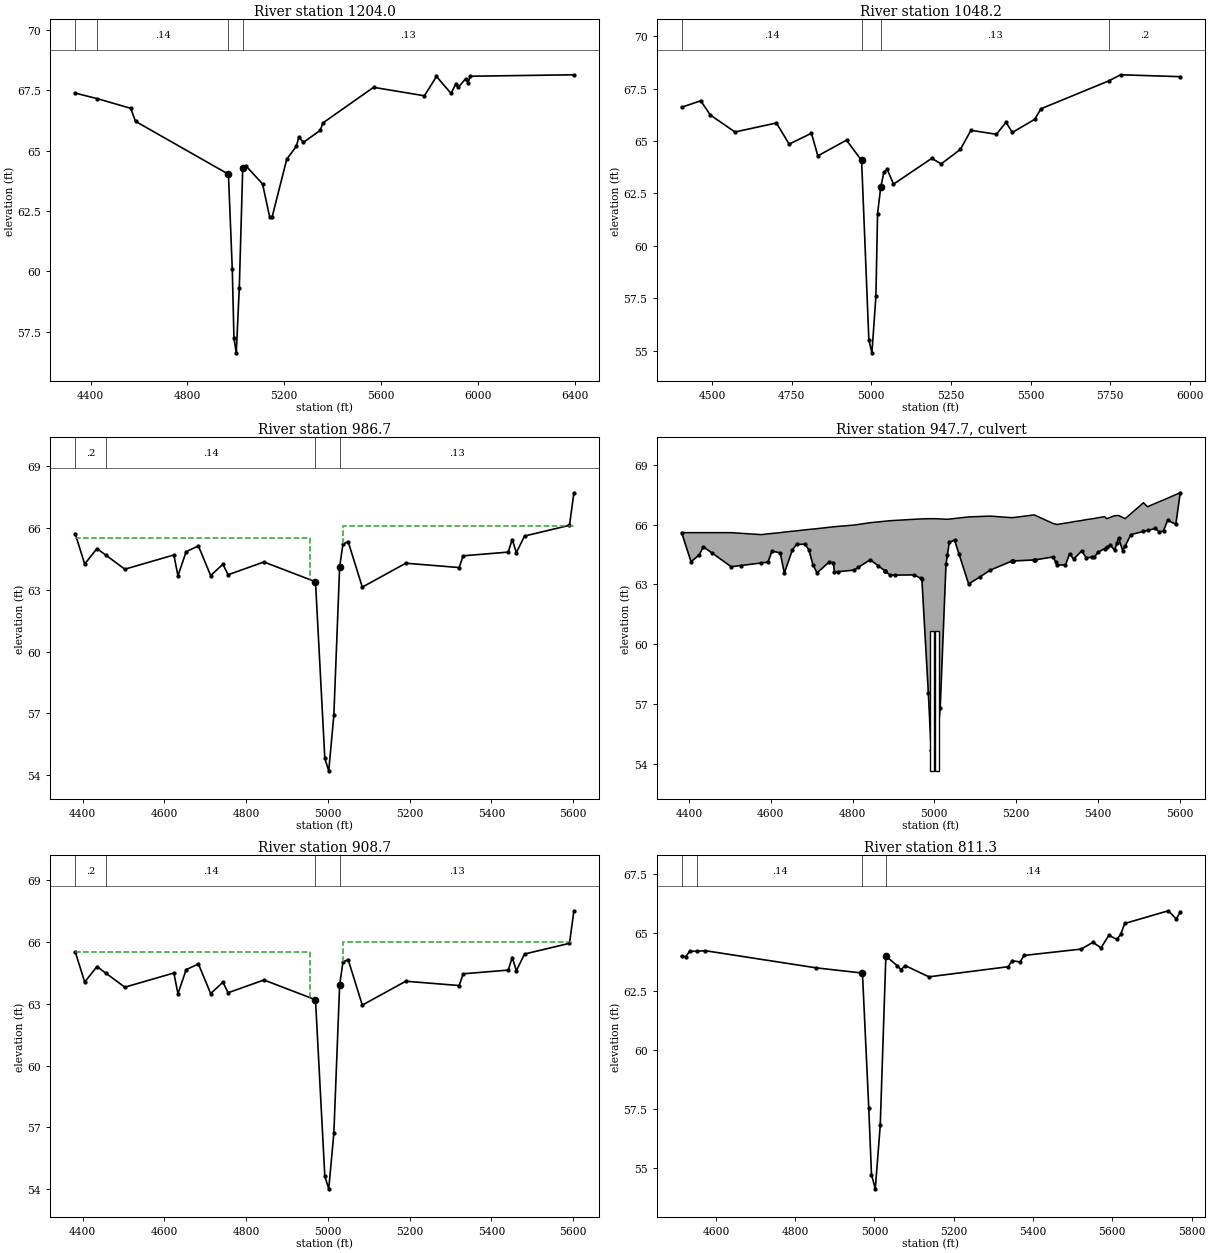
Type RM Length L Ch R = 1 ,1204.0  ,149.2,155.8,159
BEGIN DESCRIPTION:
Cross Section 1204.0-Interpolated
END DESCRIPTION:
XS GIS Cut Line= 6
      3155124.41     13916710.85      3154988.21     13916565.74
      3154536.82     13916510.18       3154252.1     13916461.57
      3153474.32     13916225.46      3153175.71     13916162.96
#Sta/Elev= 30
  4336.7   67.38  4428.2   67.15  4565.7   66.75  4585.7   66.21  4969.6   64.02
  4985.5   60.08  4992.4   57.23    5002   56.62  5014.5   59.32  5028.7   64.27
  5040.5   64.38  5110.5   63.62  5140.5   62.23  5150.5   62.26  5210.5   64.64
  5250.5   65.18  5260.5   65.56  5279.4   65.34  5349.4   65.84  5359.4   66.14
  5569.4   67.62  5779.4   67.27  5829.4   68.07  5889.4   67.37  5909.4   67.76
  5919.4   67.62  5949.4   67.97  5959.4    67.8  5969.4   68.08  6397.3   68.14
#Mann= 4 , 1 , 0
  4336.7      .2       0  4428.2     .14       0  4969.6     .05       0
  5028.7     .13       0
Bank Sta=4969.6,5028.7
XS Rating Curve= 0
Exp/Cntr=.3,.1

Type RM Length L Ch R = 1 ,1048.2  ,63.3,61.5,59.7
BEGIN DESCRIPTION:
Cross Section 1048.2-Interpolated
END DESCRIPTION:
XS GIS Cut Line= 6
      3155095.47      13916555.1      3155003.22     13916499.99
       3154538.3     13916353.42      3154265.07      13916279.1
      3153832.28      13916156.7      3153607.21     13916081.61
#Sta/Elev= 30
  4404.7   66.61  4464.7   66.92  4494.7   66.24  4572.2   65.43  4702.2   65.86
  4742.2   64.85  4812.2   65.37  4832.2   64.29  4922.2   65.04  4969.6   64.07
  4992.4    55.5    5002   54.89  5014.5   57.59  5019.7   61.53  5029.7    62.8
  5039.7   63.52  5049.7   63.66  5069.7   62.94  5189.7   64.17  5219.7   63.91
  5279.7    64.6  5312.8   65.51  5392.8   65.32  5422.8   65.89  5442.8   65.41
  5512.8   66.03  5532.8   66.54  5745.7   67.87  5782.6   68.16  5969.8   68.07
#Mann= 4 , 1 , 0
  4404.7     .14       0  4969.6     .05       0  5029.7     .13       0
  5745.7      .2       0
Bank Sta=4969.6,5029.7
XS Rating Curve= 0
Exp/Cntr=.5,.3

Type RM Length L Ch R = 1 ,986.7   ,80.7,78,75.3
BEGIN DESCRIPTION:
Upstream Section of Bridge/Culvert/Weir
END DESCRIPTION:
XS GIS Cut Line= 6
       3155163.2     13916368.12      3154746.74     13916338.79
      3154587.94      13916302.7      3154453.21     13916249.76
      3154308.85     13916170.37      3154022.21     13916006.76
#Sta/Elev= 30
  4381.9   65.71  4404.9   64.25  4434.9      65  4456.9   64.68  4503.1      64
  4623.1   64.69  4633.1   63.68  4653.1   64.85  4683.1   65.13  4713.1   63.69
  4743.1   64.24  4755.8   63.73  4843.4   64.35  4969.6   63.39  4992.4   54.82
    5002   54.21  5014.5   56.91  5028.7   64.12  5036.8   65.22  5049.5   65.34
  5084.1   63.13  5190.5   64.29    5321   64.08    5331   64.65    5441   64.83
    5451   65.44    5461    64.8    5481   65.61    5591   66.13  5601.8   67.71
#Mann= 4 , 1 , 0
  4381.9      .2       0  4456.9     .14       0  4969.6     .05       0
  5028.7     .13       0
#XS Ineff= 2 , 0
       0    4957    65.5    5037       0   66.09
Permanent Ineff=
       F       F
Bank Sta=4969.6,5028.7
XS Rating Curve= 0
Exp/Cntr=.5,.3

Type RM Length L Ch R = 2 ,947.7   ,,,
BEGIN DESCRIPTION:
ATASCOCITA ROAD
Structure ID:
END DESCRIPTION:
Bridge Culvert--1,0,-1,-1, 0
Deck Dist Width WeirC Skew NumUp NumDn MinLoCord MaxHiCord MaxSubmerge Is_Ogee
10,58,3,0, 60, 60, , , .95, 0, 1,1,,
  4381.9  4404.9  4424.9  4434.9  4503.1  4576.9  4593.1  4603.1  4623.1  4633.1
  4653.1  4663.1  4683.1  4693.1  4703.1  4713.1  4743.1  4753.1  4755.8  4803.5
  4843.4  4892.4  4950.9  4969.6  4985.5  4992.4    5002  5014.5  5028.7  5036.8
  5049.5  5084.1  5137.1  5190.5  5244.6  5290.6  5300.6    5321    5331    5341
    5361    5371    5391    5401  5416.8  5421.8    5431    5441    5451    5461
  5466.8    5481  5511.8  5521.8    5541    5551    5561    5571    5591  5601.8
    65.6    65.6    65.6    65.6    65.6    65.5   65.54   65.56    65.6   65.63
   65.67   65.69   65.74   65.76   65.78    65.8   65.87   65.89    65.9   65.98
    66.1    66.2   66.27   66.29    66.3    66.3    66.3   66.29   66.27   66.28
   66.31   66.39   66.43   66.35   66.49   66.06   66.01   66.08   66.11   66.15
   66.21   66.25   66.31   66.35    66.4    66.3   66.37   66.45   66.46   66.36
    66.3   66.55    67.1    66.9   67.07   67.16   67.24   67.33   67.51    67.6
    65.6   64.14   64.48   64.89   63.89   64.08   64.12   64.68   64.58   63.57
   64.74   65.01   65.02   64.75   63.99   63.58   64.13   64.09   63.62   63.72
   64.24   63.47   63.48   63.28   57.56   54.71    54.1    56.8   64.01   65.11
   65.23   63.02   63.72   64.18   64.23   64.38   63.99   63.97   64.54   64.27
   64.69   64.35   64.36   64.62    64.8   64.86   64.97   64.72   65.33   64.69
   64.92    65.5   65.66   65.71   65.81   65.62    65.7   66.22   66.02    67.6
  4381.9  4404.9  4424.9  4434.9  4503.1  4576.9  4593.1  4603.1  4623.1  4633.1
  4653.1  4663.1  4683.1  4693.1  4703.1  4713.1  4743.1  4753.1  4755.8  4803.5
  4843.4  4892.4  4950.9  4969.6  4985.5  4992.4    5002  5014.5  5028.7  5036.8
  5049.5  5084.1  5137.1  5190.5  5244.6  5290.6  5300.6    5321    5331    5341
    5361    5371    5391    5401  5416.8  5421.8    5431    5441    5451    5461
  5466.8    5481  5511.8  5521.8    5541    5551    5561    5571    5591  5601.8
    65.6    65.6    65.6    65.6    65.6    65.5   65.54   65.56    65.6   65.63
   65.67   65.69   65.74   65.76   65.78    65.8   65.87   65.89    65.9   65.98
    66.1    66.2   66.27   66.29    66.3    66.3    66.3   66.29   66.27   66.28
   66.31   66.39   66.43   66.35   66.49   66.06   66.01   66.08   66.11   66.15
   66.21   66.25   66.31   66.35    66.4    66.3   66.37   66.45   66.46   66.36
    66.3   66.55    67.1    66.9   67.07   67.16   67.24   67.33   67.51    67.6
   65.51   64.05   64.39    64.8    63.8   63.99   64.03   64.59   64.49   63.48
   64.65   64.92   64.93   64.66    63.9   63.49   64.04      64   63.53   63.63
   64.15   63.38   63.39   63.19   57.47   54.62   54.01   56.71   63.92   65.02
   65.14   62.93   63.63   64.09   64.14   64.29    63.9   63.88   64.45   64.18
    64.6   64.26   64.27   64.53   64.71   64.77   64.88   64.63   65.24    64.6
   64.83   65.41   65.57   65.62   65.72   65.53   65.61   66.13   65.93   67.51
BR Coef= 1 , 0 , 0 ,1.25, 0 ,,,.8,-1,2,0,
WSPro=,,,, 1 ,,,, 0 ,,,, 0 ,,,,-1 ,-1 ,-1 , 0 , 0 , 0 , 0 , 0
Culvert=2,7,10,58,.015,.4,1,8,1,53.65,4993.7,53.58,4993.7,Culvert #1  , 0 ,10
Culvert Bottom n=.015
Culvert=2,7,10,58,.015,.4,1,8,1,53.65,5007.1,53.58,5007.1,Culvert #2  , 0 ,10
Culvert Bottom n=.015
BR U #Sta/Elev= 83
  4381.9    65.6  4404.9   64.14  4424.9   64.48  4434.9   64.89  4456.9   64.57
  4503.1   63.89  4526.9   63.95  4576.9   64.08  4593.1   64.12  4603.1   64.68
  4623.1   64.58  4633.1   63.57  4653.1   64.74  4663.1   65.01  4683.1   65.02
  4693.1   64.75  4703.1   63.99  4713.1   63.58  4743.1   64.13  4753.1   64.09
  4755.8   63.62    4765   63.64  4803.5   63.72  4814.1   63.86  4843.4   64.24
  4862.7   63.94 4879.89   63.67    4880   63.66 4880.11   63.66  4892.4   63.47
  4903.9   63.47  4950.9   63.48  4966.7   63.31  4969.6   63.28  4985.5   57.56
  4992.4   54.71  4999.6   54.25    5002    54.1  5014.5    56.8  5028.7   64.01
  5032.1   64.47  5036.8   65.11  5049.5   65.23  5060.6   64.52  5084.1   63.02
  5112.3   63.39  5137.1   63.72  5190.5   64.18  5190.6   64.18 5193.59   64.18
  5193.7   64.18 5193.81   64.18  5244.6   64.23  5245.6   64.23  5245.7   64.23
  5290.6   64.38  5296.8   64.14  5300.6   63.99    5321   63.97    5331   64.54
    5341   64.27    5361   64.69    5371   64.35  5386.8   64.36    5391   64.36
    5401   64.62  5416.8    64.8  5421.8   64.86    5431   64.97    5441   64.72
  5446.8   65.07    5451   65.33    5461   64.69  5466.8   64.92    5481    65.5
  5511.8   65.66  5521.8   65.71    5541   65.81    5551   65.62    5561    65.7
    5571   66.22    5591   66.02  5601.8    67.6
BR U #Mann= 4
  4381.9      .2  4456.9     .14  4969.6     .05  5028.7     .13
BR U Banks=4969.6,5028.7
BR D #Sta/Elev= 83
  4381.9   65.51  4404.9   64.05  4424.9   64.39  4434.9    64.8  4456.9   64.48
  4503.1    63.8  4526.9   63.86  4576.9   63.99  4593.1   64.03  4603.1   64.59
  4623.1   64.49  4633.1   63.48  4653.1   64.65  4663.1   64.92  4683.1   64.93
  4693.1   64.66  4703.1    63.9  4713.1   63.49  4743.1   64.04  4753.1      64
  4755.8   63.53    4765   63.55  4803.5   63.63  4814.1   63.77  4843.4   64.15
  4862.7   63.85 4879.89   63.58    4880   63.57 4880.11   63.57  4892.4   63.38
  4903.9   63.38  4950.9   63.39  4966.7   63.22  4969.6   63.19  4985.5   57.47
  4992.4   54.62  4999.6   54.16    5002   54.01  5014.5   56.71  5028.7   63.92
  5032.1   64.38  5036.8   65.02  5049.5   65.14  5060.6   64.43  5084.1   62.93
  5112.3    63.3  5137.1   63.63  5190.5   64.09  5190.6   64.09 5193.59   64.09
  5193.7   64.09 5193.81   64.09  5244.6   64.14  5245.6   64.14  5245.7   64.14
  5290.6   64.29  5296.8   64.05  5300.6    63.9    5321   63.88    5331   64.45
    5341   64.18    5361    64.6    5371   64.26  5386.8   64.27    5391   64.27
    5401   64.53  5416.8   64.71  5421.8   64.77    5431   64.88    5441   64.63
  5446.8   64.98    5451   65.24    5461    64.6  5466.8   64.83    5481   65.41
  5511.8   65.57  5521.8   65.62    5541   65.72    5551   65.53    5561   65.61
    5571   66.13    5591   65.93  5601.8   67.51
BR D #Mann= 4
  4381.9      .2  4456.9     .14  4969.6     .05  5028.7     .13
BR D Banks=4969.6,5028.7
BC Design=,, 0 ,, 0 ,,,,,,

Type RM Length L Ch R = 1 ,908.7   ,96.3,97.4,99.1
BEGIN DESCRIPTION:
Downstream Section of Bridge/Culvert/Weir
END DESCRIPTION:
XS GIS Cut Line= 6
      3155195.21     13916296.99      3154778.74     13916267.67
      3154619.94     13916231.58      3154485.21     13916178.64
      3154340.85     13916099.25      3154054.22     13915935.63
#Sta/Elev= 30
  4381.9   65.52  4404.9   64.06  4434.9   64.81  4456.9   64.49  4503.1   63.81
  4623.1    64.5  4633.1   63.49  4653.1   64.66  4683.1   64.94  4713.1    63.5
  4743.1   64.05  4755.8   63.54  4843.4   64.16  4969.6    63.2  4992.4   54.63
    5002   54.02  5014.5   56.72  5028.7   63.93  5036.8   65.03  5049.5   65.15
  5084.1   62.94  5190.5    64.1    5321   63.89    5331   64.46    5441   64.64
    5451   65.25    5461   64.61    5481   65.42    5591   65.94  5601.8   67.52
#Mann= 4 , 1 , 0
  4381.9      .2       0  4456.9     .14       0  4969.6     .05       0
  5028.7     .13       0
#XS Ineff= 2 , 0
       0    4957    65.5    5037       0   66.01
Permanent Ineff=
       F       F
Bank Sta=4969.6,5028.7
XS Rating Curve= 0
Exp/Cntr=.5,.3

Type RM Length L Ch R = 1 ,811.3   ,0,0,0
BEGIN DESCRIPTION:
Cross Section 811.3-Interpolated
END DESCRIPTION:
XS GIS Cut Line= 5
      3155118.27      13916261.9        3155063.     13916237.96
      3154649.02      13916148.8      3154180.92     13915913.15
      3153937.92     13915854.13
#Sta/Elev= 30
  4513.5   64.01  4523.5   63.97  4533.5    64.2    4551   64.21  4573.7   64.23
  4853.7    63.5  4969.6   63.28  4985.5   57.56  4992.4   54.71    5002    54.1
  5014.5    56.8  5028.7   64.01  5057.2   63.59  5067.2   63.43  5077.2    63.6
  5137.2   63.12  5337.2   63.55  5347.2   63.81  5367.2   63.75  5377.2   64.03
  5521.3    64.3  5551.3   64.59  5571.3   64.35  5591.3   64.89  5611.3   64.71
  5621.3   64.94  5631.3   65.39  5741.3   65.93  5761.3   65.58  5771.3   65.88
#Mann= 4 , 1 , 0
  4513.5     .14       0    4551     .14       0  4969.6     .05       0
  5028.7     .14       0
Bank Sta=4969.6,5028.7
XS Rating Curve= 0
Exp/Cntr=.3,.1

Chan Stop Cuts=-1